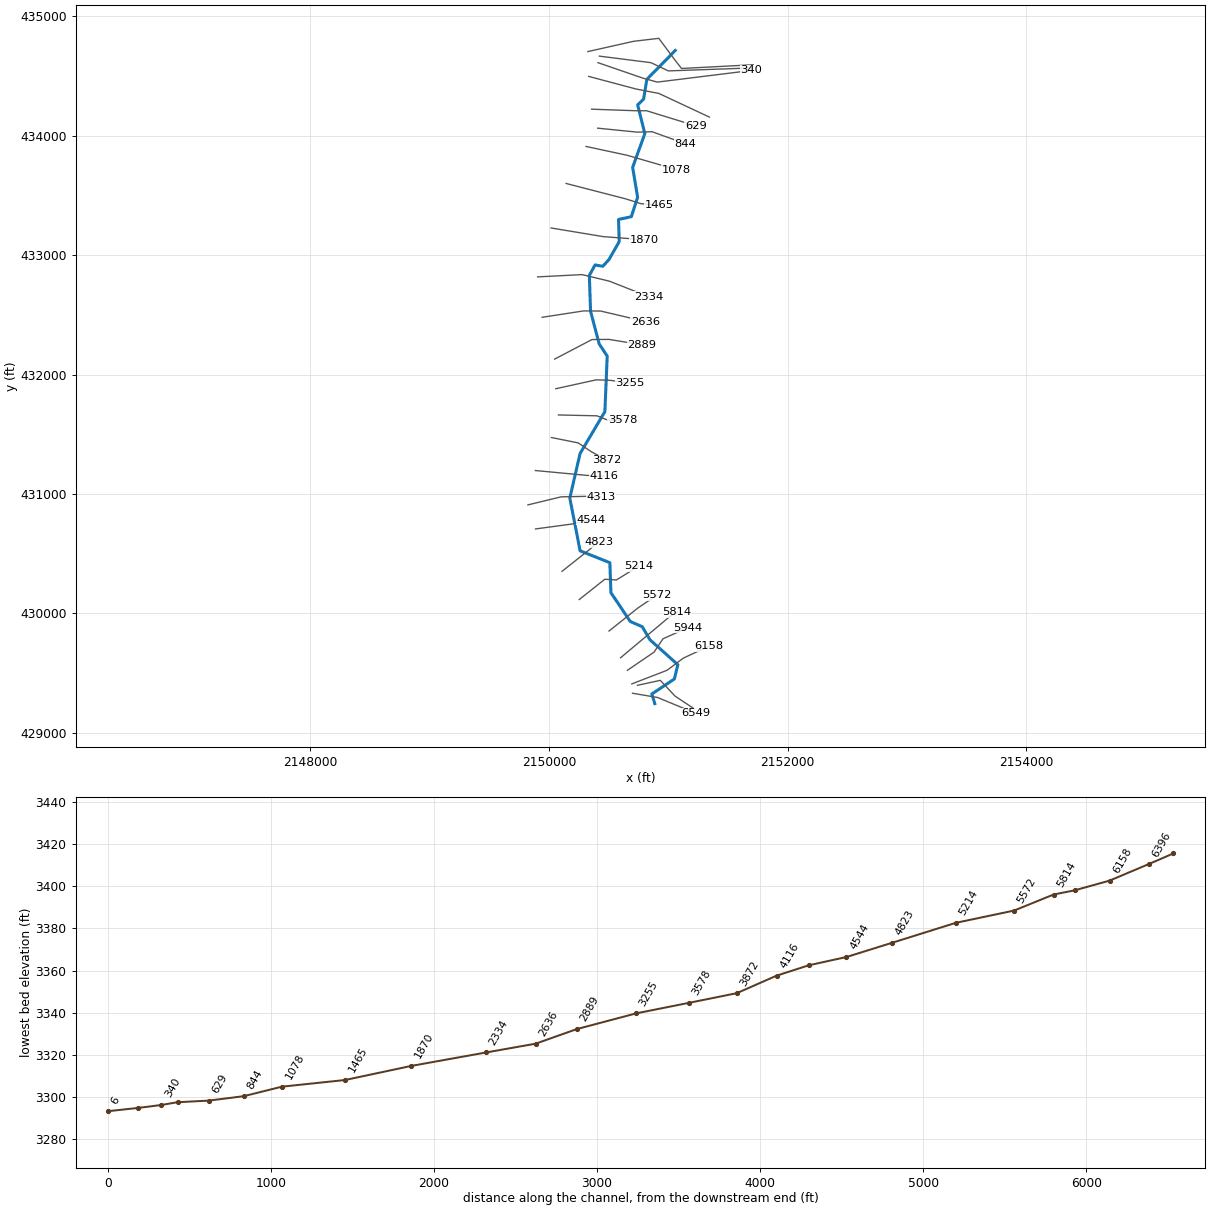
--- BEARRN.prj (project) ---

Proj Title=BEARRN
Current Plan=p01
Default Exp/Contr=0,0
English Units
Geom File=g01
Flow File=f01
Plan File=p01
BEGIN DESCRIPTION:
Stream Name- Bear Run
Flood Zone: Zone A
Greenbrier County, WV
County-Wide Study
WVDHSEM-2018-3, Flood Risk Project
HEC-RAS Version: 5.0.7
General Notes:
For the Hydrology Regression was used.
END DESCRIPTION:
DSS File=dss
DSS Export Rating Curves= 0
DSS Export Rating Curve Sorted= 0
DSS Export Volume Flow Curves= 0
DXF OffsetX= 0
DXF OffsetY= 0
DXF ScaleX= 0
DXF ScaleY= 0

--- BEARRN.p01 (plan) ---

Plan Title=Floodplain
Program Version=5.07
Short Identifier=Floodplain
Geom File=g01
Flow File=f01
Subcritical Flow
K Sum by GR= 0
Std Step Tol= 0.01
Critical Tol= 0.01
Num of Std Step Trials= 20
Max Error Tol= 0.3
Flow Tol Ratio= 0.001
Split Flow NTrial= 30
Split Flow Tol= 0.02
Split Flow Ratio= 0.02
Log Output Level= 0
Friction Slope Method= 1
Unsteady Friction Slope Method= 2
Unsteady Bridges Friction Slope Method= 1
Parabolic Critical Depth
Global Vel Dist= 0 , 0 , 0
Global Log Level= 0
CheckData=False
Encroach Param=-1 ,0,0, 0
Computation Interval=0.1SEC
Output Interval=1MIN
Instantaneous Interval=Max Profile
Mapping Interval=1HOUR
Computation Time Step Use Courant=        0
Computation Time Step Use Time Series=    0
Computation Time Step Count To Double=0
Computation Time Step Max Doubling=0
Computation Time Step Max Halving=0
Computation Time Step Residence Courant=0
Run HTab= 0
Run UNet= 0
Run Sediment= 0
Run PostProcess= 0
Run WQNet= 0
Run RASMapper= 0
UNET Theta= 0
UNET Theta Warmup= 0
UNET ZTol= 0
UNET ZSATol= 0
UNET MxIter= 0
UNET Max Iter WO Improvement= 0
UNET MaxInSteps= 0
UNET DtIC= 0
UNET DtMin= 0
UNET MaxCRTS= 0
UNET WFStab= 0
UNET SFStab= 0
UNET WFX= 1
UNET SFX= 1
UNET 1D Methodology=Finite Difference
UNET DSS MLevel= 1
UNET Pardiso=0
UNET DZMax Abort= 0
UNET Use Existing IB Tables= 0
UNET Froude Reduction=False
UNET Froude Limit= 0
UNET Froude Power= 0
UNET D1 Cores= 0
UNET D2 Coriolis=0
UNET D2 Cores= 0
UNET D2 Theta= 1
UNET D2 Theta Warmup= 1
UNET D2 Z Tol= 0.01
UNET D2 Volume Tol= 0.01
UNET D2 Max Iterations= 20
UNET D2 Equation= 0
UNET D2 RampUpFraction=0.1
UNET D2 TimeSlices= 1
UNET D2 BCVolumeCheck=0
UNET D1D2 MaxIter= 0
UNET D1D2 ZTol=0.01
UNET D1D2 QTol=0.1
UNET D1D2 MinQTol=1
DSS File=dss
Write IC File= 0
Write IC File at Fixed DateTime=0
Write IC File at Sim End=0
Echo Input=False
Echo Parameters=False
Echo Output=False
Write Detailed= 0
HDF Write Warmup=0
HDF Write Time Slices=0
HDF Flush=0
HDF Face Node Velocities=0
HDF Compression= 1
HDF Chunk Size= 1
HDF Spatial Parts= 1
HDF Use Max Rows=0
HDF Fixed Rows= 1
Calibration Method= 0
Calibration Iterations= 20
Calibration Max Change=0.05
Calibration Tolerance=0.2
Calibration Maximum=1.5
Calibration Minimum=0.5
Calibration Optimization Method= 1
WQ AD Non Conservative
WQ ULTIMATE=-1
WQ Max Comp Step=1HOUR
WQ Output Interval=15MIN
WQ Output Selected Increments= 0
WQ Output face flow=0
WQ Output face velocity=0
WQ Output face area=0
WQ Output face dispersion=0
WQ Output cell volume=0
WQ Output cell surface area=0
WQ Output cell continuity=0
WQ Output cumulative cell continuity=0
WQ Output face conc=0
WQ Output face dconc_dx=0
WQ Output face courant=0
WQ Output face peclet=0
WQ Output face adv mass=0
WQ Output face disp mass=0
WQ Output cell mass=0
WQ Output cell source sink temp=0
WQ Output nsm pathways=0
WQ Output nsm derived pathways=0
WQ Output MaxMinRange=-1
WQ Daily Max Min Mean=-1
WQ Daily Range=0
WQ Daily Time=0
WQ Create Restart=0
WQ Fixed Restart=0
WQ System Summary=0
WQ Write To DSS=0
WQ Use Fixed Temperature=0
Sorting and Armoring Iterations= 10
XS Update Threshold= 0.02
Bed Roughness Predictor= 0
Hydraulics Update Threshold= 0.02
Energy Slope Method= 1
Volume Change Method= 1
Sediment Retention Method= 0
XS Weighting Method= 0
Number of US Weighted Cross Sections= 1
Number of DS Weighted Cross Sections= 1
Upstream XS Weight=0
Main XS Weight=1
Downstream XS Weight=0
Number of DS XS's Weighted with US Boundary= 1
Upstream Boundary Weight= 1
Weight of XSs Associated with US Boundary= 0
Number of US XS's Weighted with DS Boundary= 1
Downstream Boundary Weight= 0.5
Weight of XSs Associated with DS Boundary= 0.5
Percentile Method= 0
Sediment Output Level= 3
Mass or Volume Output= 0
Output Increment Type= 1
Profile and TS Output Increment= 1
XS Output Flag= 0
XS Output Increment= 10
Write Gradation File= 0
Read Gradation Hotstart= 0
Write HDF5 File= 1
Write Binary Output= 1
Write DSS Sediment File= 0
SV Curve= 0
Specific Gage Flag= 0

--- BEARRN.f01 (steady flow) ---

Flow Title=NFF Regression Equation
Program Version=5.07
Number of Profiles= 6
Profile Names=f1p,f10p,f4p,f2p,f02p,f1pplus
River Rch & RM=BEARRN,Main            ,6549
     412     215     288     348     579     610
River Rch & RM=BEARRN,Main            ,6158
     672     357     474     570     936     994
River Rch & RM=BEARRN,Main            ,4313
     756     404     534     641    1050    1120
River Rch & RM=BEARRN,Main            ,1870
     844     453     598     717    1170    1250
Boundary for River Rch & Prof#=BEARRN,Main            , 1
Up Type= 0
Dn Type= 3
Dn Slope=0.01621
Boundary for River Rch & Prof#=BEARRN,Main            , 2
Up Type= 0
Dn Type= 3
Dn Slope=0.01621
Boundary for River Rch & Prof#=BEARRN,Main            , 3
Up Type= 0
Dn Type= 3
Dn Slope=0.01621
Boundary for River Rch & Prof#=BEARRN,Main            , 4
Up Type= 0
Dn Type= 3
Dn Slope=0.01621
Boundary for River Rch & Prof#=BEARRN,Main            , 5
Up Type= 0
Dn Type= 3
Dn Slope=0.01621
Boundary for River Rch & Prof#=BEARRN,Main            , 6
Up Type= 0
Dn Type= 3
Dn Slope=0.01621
DSS Import GetInterval= 0
DSS Import GetPeak= 0
DSS Import FillOption= 0

--- BEARRN.g01 (geometry) ---

Geom Title=USGS 10m DEM
Program Version=5.07

River Reach=BEARRN          ,Main
Reach XY= 30
     2150887.684429244.595000001     2150862.318      429325.079
     2151051.533429451.072000001     2151080.524      429570.646
     2150847.121      429779.134     2150782.346429888.323999999
     2150681.535      429932.475     2150519.678430173.653999999
     2150510.961      430424.412     2150261.535430523.993000001
     2150175.199430965.754000001     2150261.331      431339.271
     2150469.072      431689.089     2150488.599      432154.419
     2150421.604432255.723999999     2150349.088432529.585000001
     2150338.885      432829.999      2150386.96432917.560000001
      2150451.56      432906.418     2150503.575      432963.206
     2150589.244      433112.911     2150583.668      433298.354
      2150690.73433321.790999999     2150743.561433484.631999999
     2150701.788433734.413000001     2150803.993      434017.605
     2150743.923434258.027000001     2150793.599434305.936000001
    2150821.2351     434471.94312151059.07407954434713.602563391

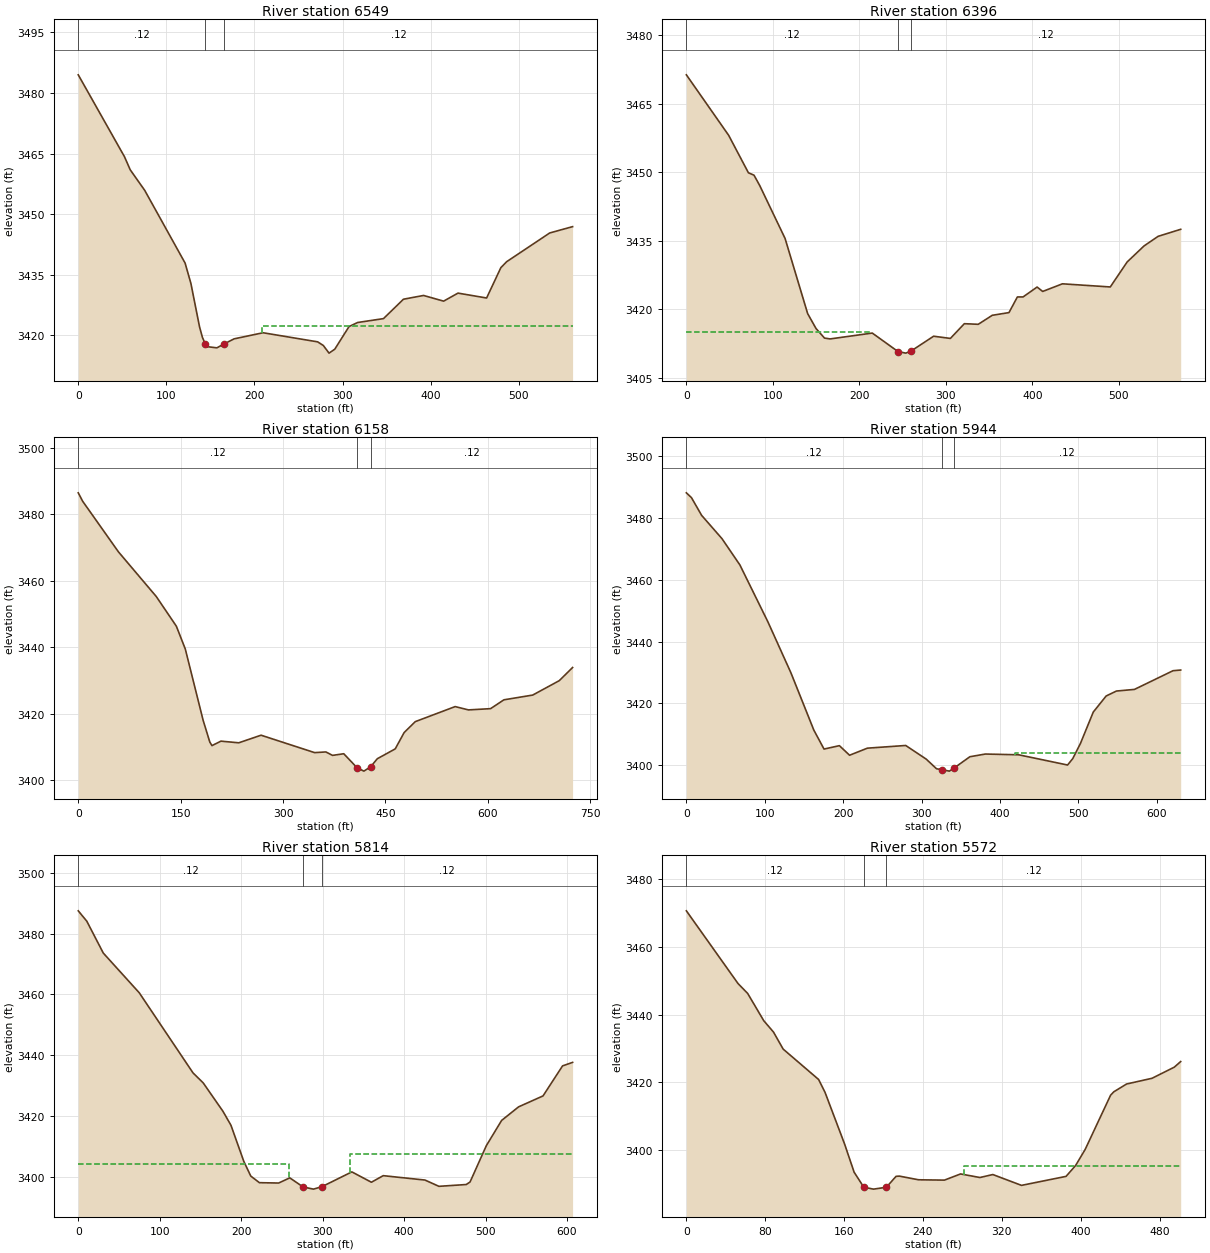
Type RM Length L Ch R = 1 ,6549    ,168.1,152.7,137.4
XS GIS Cut Line= 3
     2150700.811      429331.431     2150910.916       429295.82
     2151232.601      429162.873
#Sta/Elev= 30
       0  3484.5    52.5  3464.2      59 3460.97    75.4 3455.89   121.3 3437.85
   127.9  3432.8   137.7 3422.04     141 3419.42   144.2 3417.84   147.5 3417.11
   157.4 3416.85   165.7 3417.84     177 3419.08   209.8 3420.59   271.7 3418.34
   278.2 3417.44   284.7 3415.54   291.2 3416.51   307.4 3422.12   317.2 3423.13
   346.5 3424.09   369.2  3428.9     392 3429.83   414.8 3428.42   431.1 3430.41
   463.6  3429.2   479.8 3436.73   486.4  3438.2   535.2 3445.31   561.2 3446.88
#Mann= 3 , 0 , 0
       0     .12       0   144.2     .04       0   165.7     .12       0
#XS Ineff= 2 , 0
                          208.87         3422.24
Permanent Ineff=
       F       F
Bank Sta=144.2,165.7
XS Rating Curve= 0 ,0
Exp/Cntr=0.3,0.1

Type RM Length L Ch R = 1 ,6396    ,204.3,238.3,272.3
XS GIS Cut Line= 4
     2150742.357      429397.905     2150933.469      429439.451
      2151056.92      429307.691     2151219.544      429199.671
#Sta/Elev= 30
       0 3471.34    48.9  3458.1    71.7 3449.91    78.2 3449.37    84.8 3447.11
   114.1 3435.53   140.2 3419.08   149.9 3415.81   159.7 3413.72   166.2 3413.54
   214.9 3414.82   244.6 3410.78   253.6 3410.43   259.6 3410.87   285.8 3414.13
   305.2 3413.65   321.3 3416.87   337.4 3416.74   353.6 3418.71   372.9  3419.3
   382.6 3422.72   389.2 3422.73   405.4 3424.89   411.9 3423.93   434.7  3425.6
     490 3424.91   509.5 3430.38   529.1  3433.9   545.3 3435.99   571.4 3437.53
#Mann= 3 , 0 , 0
       0     .12       0   244.6     .04       0   259.6     .12       0
#XS Ineff= 2 , 0
          213.98 3414.96
Permanent Ineff=
       F       F
Bank Sta=244.6,259.6
XS Rating Curve= 0 ,0
Exp/Cntr=0.3,0.1

Type RM Length L Ch R = 1 ,6158    ,205.9,213.6,221.2
XS GIS Cut Line= 4
     2150694.876      429409.775     2150990.447       429523.73
     2151126.955      429625.815     2151341.808      429725.526
#Sta/Elev= 30
       0 3486.49     6.5 3483.94    58.8 3468.73   114.3 3455.25   143.7 3446.32
   156.8 3439.44   182.9 3417.98   192.7 3411.42   195.9 3410.35     209 3411.69
   235.1 3411.19   267.8 3413.48   346.3 3408.23   362.7 3408.44   372.5  3407.4
   388.9  3407.9   408.3  3403.7   418.4 3402.66   428.2 3403.96   438.1  3406.4
   464.3 3409.36   477.4 3414.29   493.7 3417.57   552.1  3422.1   571.6  3421.1
     604 3421.48   623.5 3424.14   665.7 3425.57   704.6 3429.91   724.1 3433.87
#Mann= 3 , 0 , 0
       0     .12       0   408.3     .04       0   428.2     .12       0
Bank Sta=408.3,428.2
XS Rating Curve= 0 ,0
Exp/Cntr=0.3,0.1

Type RM Length L Ch R = 1 ,5944    ,130,130,130
XS GIS Cut Line= 4
     2150658.078       429523.73      2150881.24      429675.671
     2150956.023      429787.252     2151162.566       429879.84
#Sta/Elev= 30
       0 3488.11     6.5 3486.55    19.5 3480.81    45.5 3473.26    68.3 3464.77
   104.1 3446.32   133.4 3429.86   162.6 3411.34   175.6  3405.2   195.2  3406.3
   208.2  3403.2   230.9 3405.49   279.8 3406.36     306 3401.94   319.1 3398.83
   326.4  3398.5   335.5 3398.06   341.4 3399.04   361.7 3402.72   381.4 3403.59
     424 3403.34   486.3 3400.04   492.9 3402.11   502.7 3407.01   519.1 3417.18
   535.5 3422.37   548.6 3423.97   571.6  3424.5   620.8 3430.55   630.6 3430.77
#Mann= 3 , 0 , 0
       0     .12       0   326.4     .04       0   341.4     .12       0
#XS Ineff= 2 , 0
                          419.45         3403.97
Permanent Ineff=
       F       F
Bank Sta=326.4,341.4
XS Rating Curve= 0 ,0
Exp/Cntr=0.3,0.1

Type RM Length L Ch R = 1 ,5814    ,242.7,242.7,242.7
XS GIS Cut Line= 3
 2150600.5879307429628.449213324 2151011.4691383429972.319751868
2151073.18949137430007.588525052
#Sta/Elev= 30
       0 3487.46    10.5 3484.05    30.7  3473.6    74.9 3460.54   140.9 3434.23
   153.4 3430.95   177.6 3421.64   187.5 3417.02   203.2 3405.21   211.8 3400.35
   222.4 3398.18     246 3398.06   259.7 3399.76     276 3396.78     276 3396.77
   288.8 3396.06   299.3 3396.88   335.9 3401.72   359.9 3398.32   374.4 3400.48
   425.7 3399.04   442.8 3396.98   476.3 3397.57     481 3398.39     501 3410.33
   519.8 3418.63   540.6 3423.08   570.6 3426.67   594.6 3436.54   606.9 3437.68
#Mann= 3 , 0 , 0
       0     .12       0     276     .04       0   299.3     .12       0
#XS Ineff= 2 , 0
          258.44 3404.39  333.75         3407.66
Permanent Ineff=
       F       F
Bank Sta=276,299.3
XS Rating Curve= 0 ,0
Exp/Cntr(USF)=0,0
Exp/Cntr=0.3,0.1

Type RM Length L Ch R = 1 ,5572    ,373.7,357.1,340.5
XS GIS Cut Line= 3
     2150503.764      429852.538     2150747.105      430046.024
      2150904.98      430152.857
#Sta/Elev= 30
       0 3470.71    52.4 3449.22    62.2 3446.29    78.5 3438.24    88.4 3434.87
    98.2 3429.84   134.2 3420.85   140.7 3417.04   160.4 3401.88   170.2 3393.45
     180 3389.02   189.8 3388.45   202.9    3389   212.7 3392.22     216  3392.3
   235.6 3391.21   261.8 3391.11   278.2 3392.94   297.8 3391.88   310.9 3392.76
     340 3389.56   385.2 3392.22   394.9 3395.44   404.6 3400.19   430.4 3416.22
   433.7 3417.23   446.6 3419.52   472.4 3421.21     495  3424.5   501.5 3426.16
#Mann= 3 , 0 , 0
       0     .12       0     180     .04       0   202.9     .12       0
#XS Ineff= 2 , 0
                          281.99         3395.25
Permanent Ineff=
       F       F
Bank Sta=180,202.9
XS Rating Curve= 0 ,0
Exp/Cntr=0.3,0.1

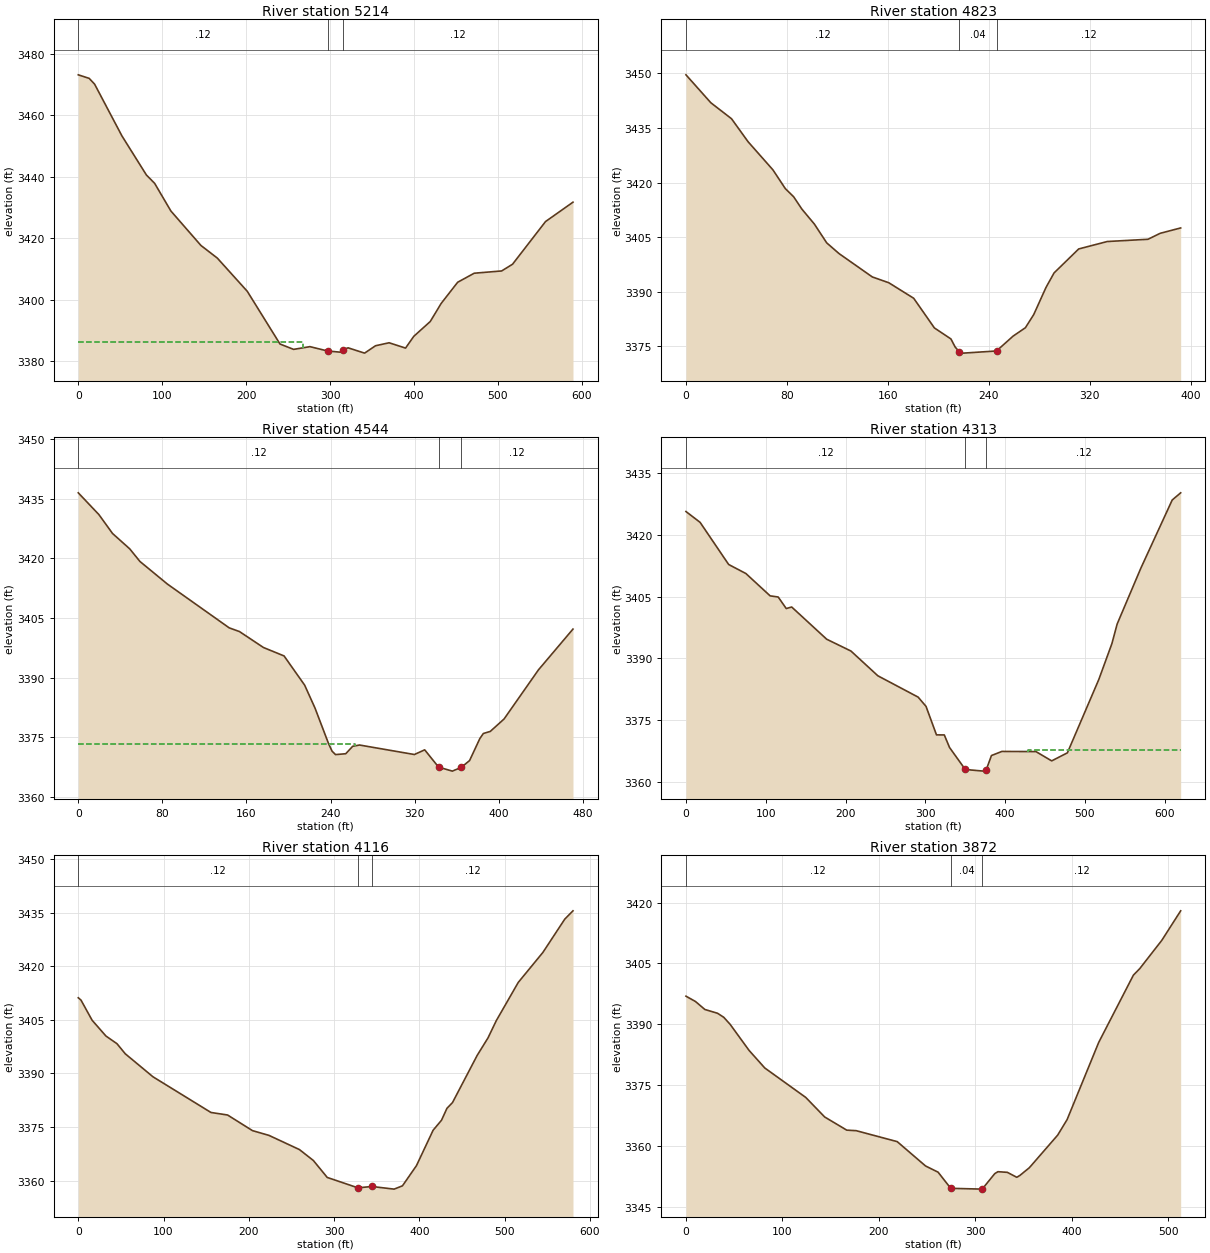
Type RM Length L Ch R = 1 ,5214    ,373.7,391.1,408.6
XS GIS Cut Line= 4
     2150254.487      430116.059     2150468.153      430285.805
     2150565.489       430279.87     2150751.853      430395.012
#Sta/Elev= 30
       0 3473.23      13 3472.08    19.5 3470.18      52 3453.36    81.2 3440.62
      91 3437.91   110.4 3428.89   146.2 3417.68   165.7 3413.57   201.4 3402.76
   240.4  3385.6   256.6 3383.86   276.1 3384.75   297.1 3383.33   311.9 3382.96
   315.1  3383.8   321.6 3384.36   341.2 3382.64   354.2 3385.04   370.4 3386.01
     390 3384.28   399.8 3388.11   419.4 3392.92   432.5 3398.84   452.1 3405.71
   471.8 3408.65   504.5 3409.39   517.5 3411.58   556.8 3425.47   589.5 3431.77
#Mann= 3 , 0 , 0
       0     .12       0   297.1     .04       0   315.1     .12       0
#XS Ineff= 2 , 0
          267.27 3386.41
Permanent Ineff=
       F       F
Bank Sta=297.1,315.1
XS Rating Curve= 0 ,0
Exp/Cntr=0.3,0.1

Type RM Length L Ch R = 1 ,4823    ,289.4,279,268.6
XS GIS Cut Line= 3
     2150109.669      430352.279     2150325.709      430523.211
     2150415.923      430596.807
#Sta/Elev= 30
       0 3449.59    19.7 3441.92    36.1 3437.53    49.2 3431.22    68.9 3423.49
    78.7 3418.35    85.3 3416.11    91.8 3412.73   101.7 3408.62   111.5 3403.45
   121.3  3400.5   147.6  3394.1   160.7  3392.5   180.4 3388.24   196.8  3380.1
   209.9 3377.07   213.2 3374.88   216.4 3373.58   219.7 3373.18     246 3373.77
   259.1 3377.84   268.9 3380.16   275.5 3383.77   285.2 3391.21   291.6  3395.2
   311.1 3401.78   333.7 3403.82     366 3404.44   375.7 3406.08   391.9 3407.55
#Mann= 3 , 0 , 0
       0     .12       0   216.4     .04       0     246     .12       0
Bank Sta=216.4,246
XS Rating Curve= 0 ,0
Exp/Cntr=0.3,0.1

Type RM Length L Ch R = 1 ,4544    ,230.8,230.8,230.8
XS GIS Cut Line= 3
     2149887.694      430707.201     2150204.632      430749.934
     2150351.823      430783.171
#Sta/Elev= 30
       0 3436.49    19.6 3431.02    32.6 3426.26      49 3422.38    58.7 3419.21
    84.8 3413.53   143.6 3402.51   153.4 3401.57   176.2 3397.56   195.8 3395.44
   215.4 3388.09   225.2 3382.35   238.2 3373.34   241.5 3371.46   244.8 3370.61
   254.5 3370.83   261.1  3372.7   267.6 3373.02   319.8 3370.63   329.6 3371.81
   342.8 3367.47   355.9 3366.45   364.3 3367.38   372.3  3369.1   382.1 3374.65
   385.4 3375.92     392 3376.44   405.1 3379.56   437.9 3391.95   470.7  3402.2
#Mann= 3 , 0 , 0
       0     .12       0   342.8     .04       0   364.3     .12       0
#XS Ineff= 2 , 0
          263.59 3373.29
Permanent Ineff=
       F       F
Bank Sta=342.8,364.3
XS Rating Curve= 0 ,0
Exp/Cntr=0.3,0.1

Type RM Length L Ch R = 1 ,4313    ,197.5,197.5,197.5
XS GIS Cut Line= 4
2149823.86939929430908.5097422742150102.53624914430975.999369971
2150326.77597988  430980.3535395 2150435.6302181430973.822285207
#Sta/Elev= 30
       0 3425.68    17.7 3423.05    53.5  3412.8    75.1  3410.6   105.5 3405.17
   115.6 3404.89   125.7 3402.08   132.5 3402.46   176.4 3394.62   206.8 3391.75
   240.5 3385.73     291 3380.54   300.9 3378.29     314 3371.36   323.8 3371.34
   330.4 3368.28   350.1 3362.94   373.1 3362.54   376.4 3362.88   382.9 3366.33
     396 3367.33   438.7 3367.29   458.4 3365.03   478.1 3366.99   517.5 3384.84
   533.9 3393.56   540.5 3398.33   570.1 3411.87   609.5 3428.49   620.1 3430.23
#Mann= 3 , 0 , 0
       0     .12       0   350.1     .04       0   376.4     .12       0
#XS Ineff= 2 , 0
                          429.13         3367.67
Permanent Ineff=
       F       F
Bank Sta=350.1,376.4
XS Rating Curve= 0 ,0
Exp/Cntr(USF)=0,0
Exp/Cntr=0.3,0.1

Type RM Length L Ch R = 1 ,4116    ,255.3,244.2,233
XS GIS Cut Line= 4
     2149886.507      431196.258     2150151.215      431171.331
     2150313.838      431155.899     2150464.592       431147.59
#Sta/Elev= 30
       0 3411.19     3.2 3410.53    16.2 3404.91    32.4 3400.49    45.4 3398.33
    55.1 3395.51    87.6 3389.07   155.6 3379.08   175.1 3378.37   204.3    3374
   223.7 3372.66   259.4 3368.69   275.7 3365.64     292 3360.89     328 3357.98
   344.3 3358.36   370.4 3357.62   380.2 3358.54   396.6 3364.18   416.2 3374.12
     426  3376.9   432.4 3380.24   438.9 3381.85   467.8 3395.04   480.6 3399.98
   490.3  3404.8     516 3415.48   544.9 3423.88   570.6 3433.21   580.2 3435.53
#Mann= 3 , 0 , 0
       0     .12       0     328     .04       0   344.3     .12       0
Bank Sta=328,344.3
XS Rating Curve= 0 ,0
Exp/Cntr=0.3,0.1

Type RM Length L Ch R = 1 ,3872    ,289.7,293.9,298.2
XS GIS Cut Line= 4
     2150020.642      431472.837     2150244.991       431427.73
     2150358.946       431351.76     2150488.332      431281.725
#Sta/Elev= 30
       0 3396.92     9.8 3395.62    19.6 3393.64    32.7 3392.71    39.2 3391.71
    45.8 3389.97    65.4 3383.55    81.7 3379.21   124.2 3371.94   143.8 3367.12
   166.7 3363.87   176.5 3363.74     219 3361.04   248.4 3355.03   261.4  3353.5
   274.5 3349.52   307.1 3349.32   320.1 3353.13   323.4 3353.62   333.2 3353.46
     343 3352.24   346.2  3352.7     356  3354.6   385.4 3362.65   395.2  3366.5
   427.9 3385.51   463.9 3402.12   470.4  3403.7   493.3 3410.69   512.9 3417.98
#Mann= 3 , 0 , 0
       0     .12       0   274.5     .04       0   307.1     .12       0
#XS Ineff= 2 , 0
                          331.96         3353.29
Permanent Ineff=
       F       F
Bank Sta=274.5,307.1
XS Rating Curve= 0 ,0
Exp/Cntr=0.3,0.1

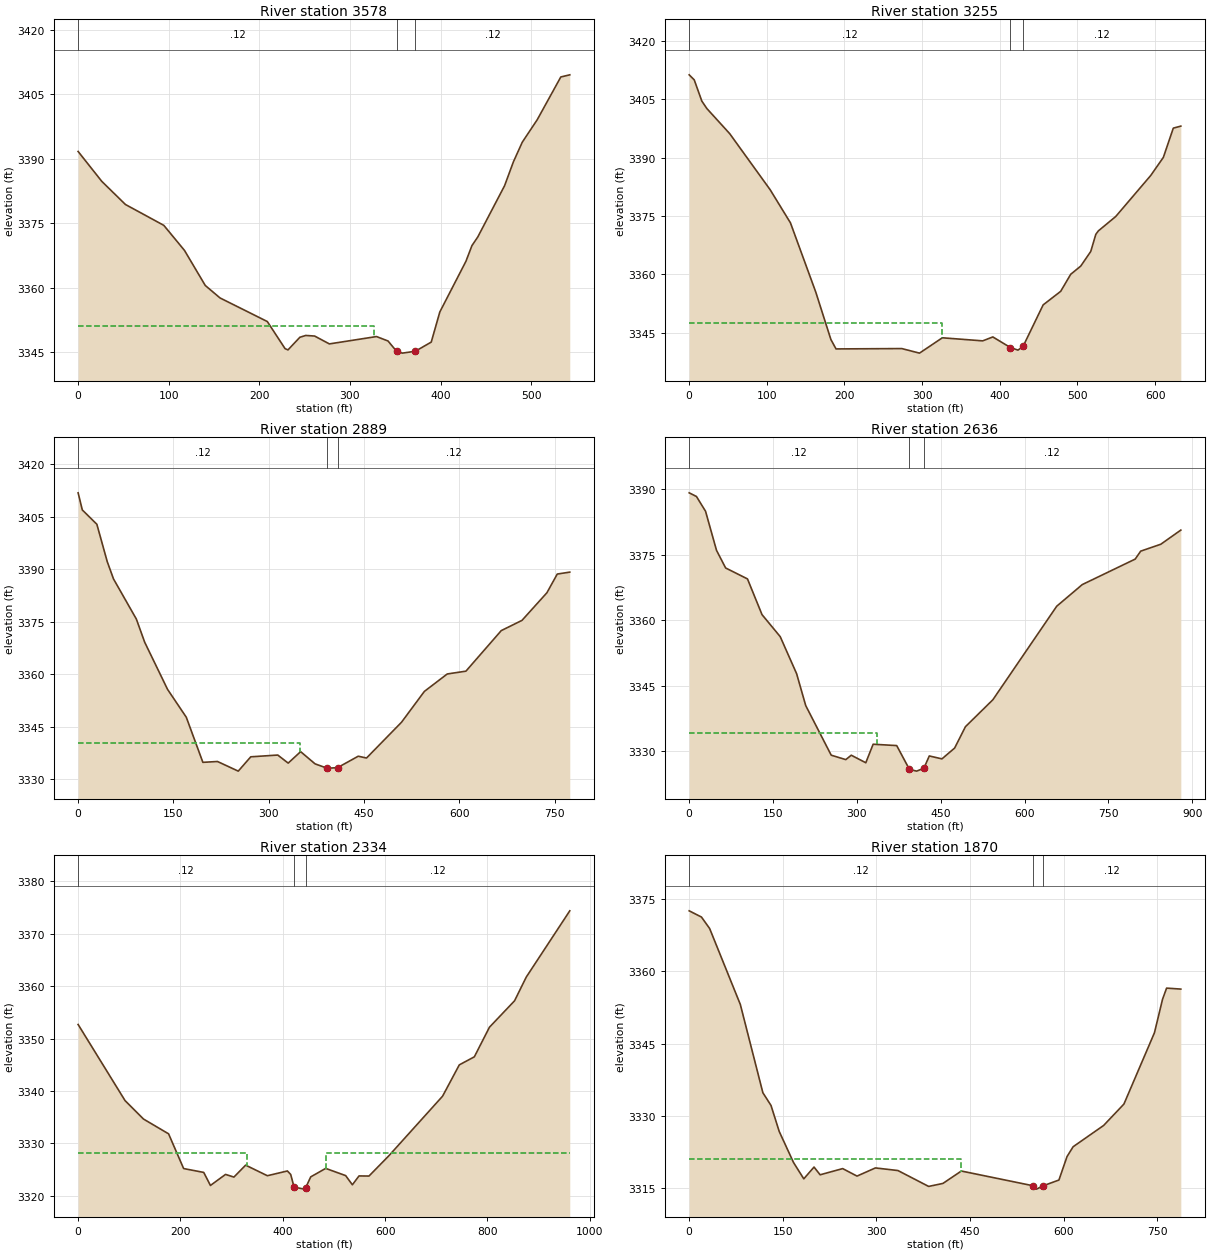
Type RM Length L Ch R = 1 ,3578    ,315.6,323.3,331
XS GIS Cut Line= 4
     2150079.993      431661.575     2150402.866      431654.453
     2150494.267      431617.655     2150615.345      431617.655
#Sta/Elev= 30
       0 3391.71    26.1 3384.75    52.2 3379.36    94.6 3374.49   117.4 3368.65
   140.3 3360.49   156.6 3357.58   208.8 3352.08   228.4 3345.76   231.6 3345.47
   244.7 3348.41   251.2 3348.84     261  3348.7   277.3 3346.87   329.3 3348.58
     342 3347.55   351.6 3345.12   357.9 3344.72   372.2 3345.16   389.7 3347.29
   399.2 3354.32     428 3366.12   434.6 3369.76   441.1  3371.8   470.6 3383.71
   480.4  3389.3   490.2 3393.88   506.6 3399.08   532.7 3409.07   542.6 3409.57
#Mann= 3 , 0 , 0
       0     .12       0   351.6     .04       0   372.2     .12       0
#XS Ineff= 2 , 0
          326.84 3351.05
Permanent Ineff=
       F       F
Bank Sta=351.6,372.2
XS Rating Curve= 0 ,0
Exp/Cntr=0.3,0.1

Type RM Length L Ch R = 1 ,3255    ,362.7,363.8,365
XS GIS Cut Line= 4
      2150057.44      431881.176     2150398.118      431955.959
     2150518.008      431951.211     2150680.631       431927.47
#Sta/Elev= 30
       0 3411.25     6.5 3409.96    16.3  3404.5    22.8 3402.58    52.2 3396.13
   104.3 3381.72   130.4 3373.22     163 3355.43   182.5 3343.23   189.1 3340.82
   273.8 3340.91   296.6 3339.74     326 3343.68     378 3342.89     391  3343.9
   413.6 3341.18   423.4 3340.51   429.9 3341.45   455.8 3352.13   478.4 3355.62
   491.3    3360   504.2  3362.1   517.1 3365.86   523.6 3370.25   526.8 3371.13
   549.3 3374.85   594.4  3385.4   610.6 3390.04   623.4 3397.55   633.1 3398.07
#Mann= 3 , 0 , 0
       0     .12       0   413.6     .04       0   429.9     .12       0
#XS Ineff= 2 , 0
          325.58 3347.48
Permanent Ineff=
       F       F
Bank Sta=413.6,429.9
XS Rating Curve= 0 ,0
Exp/Cntr=0.3,0.1

Type RM Length L Ch R = 1 ,2889    ,253.3,253,252.6
XS GIS Cut Line= 4
     2150047.943      432129.266      2150361.32      432293.076
     2150503.764      432294.263     2150777.968      432249.156
#Sta/Elev= 30
       0 3411.79     6.6  3406.9    29.5 3402.81    45.8 3392.16    55.7  3387.2
    91.7 3375.72   104.8 3369.12   140.8 3355.65   170.3 3347.69   196.4 3334.81
   219.4 3335.05   252.1  3332.3   271.8 3336.39   314.3 3336.89   330.7 3334.59
   350.3 3337.86     373 3334.38   392.5  3333.1   408.6 3333.31     441 3336.56
     454 3336.04   509.1 3346.26   545.1 3355.07   581.1 3360.05   610.5 3360.85
   666.1 3372.43   698.8 3375.36     738 3383.25   754.3 3388.59     774 3389.14
#Mann= 3 , 0 , 0
       0     .12       0   392.5     .04       0   408.6     .12       0
#XS Ineff= 2 , 0
          349.94 3340.33
Permanent Ineff=
       F       F
Bank Sta=392.5,408.6
XS Rating Curve= 0 ,0
Exp/Cntr=0.3,0.1

Type RM Length L Ch R = 1 ,2636    ,307.7,302.3,296.8
XS GIS Cut Line= 4
     2149943.484       432479.44     2150291.285      432532.856
     2150433.729      432531.669     2150808.831      432443.829
#Sta/Elev= 30
       0 3389.22      13 3388.38    29.3 3384.99    48.9 3376.03    65.2 3371.98
   104.3 3369.47   130.3 3361.28   162.9 3356.22   192.2 3347.73   208.5 3340.41
   254.1 3329.03   280.2 3328.01     290 3329.02     316 3327.29   329.1 3331.54
   371.3 3331.23     394 3325.78   406.9 3325.37   419.9 3326.03   429.6 3328.85
   452.2 3328.18   474.9 3330.66   494.3 3335.57   543.3 3341.74   657.6 3363.21
   703.3 3368.17     798 3374.02   807.8 3375.84   843.7 3377.42   879.6 3380.67
#Mann= 3 , 0 , 0
       0     .12       0     394     .04       0   419.9     .12       0
#XS Ineff= 2 , 0
          335.55 3334.23
Permanent Ineff=
       F       F
Bank Sta=394,419.9
XS Rating Curve= 0 ,0
Exp/Cntr=0.3,0.1

Type RM Length L Ch R = 1 ,2334    ,453.9,458.6,462.5
XS GIS Cut Line= 4
     2149905.499      432817.744     2150278.228      432836.737
     2150506.138      432782.133     2150834.945      432652.747
#Sta/Elev= 30
       0 3352.68    91.7 3338.15   127.7 3334.63   176.8  3331.8   206.2 3325.17
   245.5 3324.43   258.6 3321.94   288.1 3324.05   304.5 3323.54   327.4 3325.82
   369.9  3323.8     409 3324.71   415.5 3324.04     422 3321.64   441.6 3321.24
   444.8 3321.51   454.6 3323.58   483.9  3325.2   522.9 3323.82     536 3322.07
     549 3323.76   568.5 3323.74   607.6 3327.64   712.3 3338.99     745 3344.97
   774.4 3346.51   803.9 3352.16     853 3357.21   875.8 3361.73   960.9 3374.39
#Mann= 3 , 0 , 0
       0     .12       0     422     .04       0   444.8     .12       0
#XS Ineff= 2 , 0
          330.01 3328.17  484.71         3328.06
Permanent Ineff=
       F       F
Bank Sta=422,444.8
XS Rating Curve= 0 ,0
Exp/Cntr=0.3,0.1

Type RM Length L Ch R = 1 ,1870    ,410.4,407.5,404
XS GIS Cut Line= 3
     2150018.268       433227.27     2150455.095      433154.861
     2150799.335      433128.746
#Sta/Elev= 30
       0  3372.5    19.7 3371.21    32.8 3368.84      82  3353.1   118.1 3334.83
   131.2 3332.18   144.3 3326.81   167.3 3320.36   183.7 3316.99   200.1 3319.43
   209.9 3317.83     246 3319.11     269 3317.56   298.5 3319.25   334.6 3318.71
   383.8 3315.42   406.7 3316.04   436.2 3318.61   550.3 3315.58   556.8 3314.86
   566.6 3315.52   592.6 3316.74   605.6  3321.6   615.4 3323.64   664.3 3328.05
   696.8 3332.48   745.7 3347.24   758.7 3354.19   765.2 3356.49     788 3356.29
#Mann= 3 , 0 , 0
       0     .12       0   550.3     .04       0   566.6     .12       0
#XS Ineff= 2 , 0
          434.99 3321.05
Permanent Ineff=
       F       F
Bank Sta=550.3,566.6
XS Rating Curve= 0 ,0
Exp/Cntr=0.3,0.1

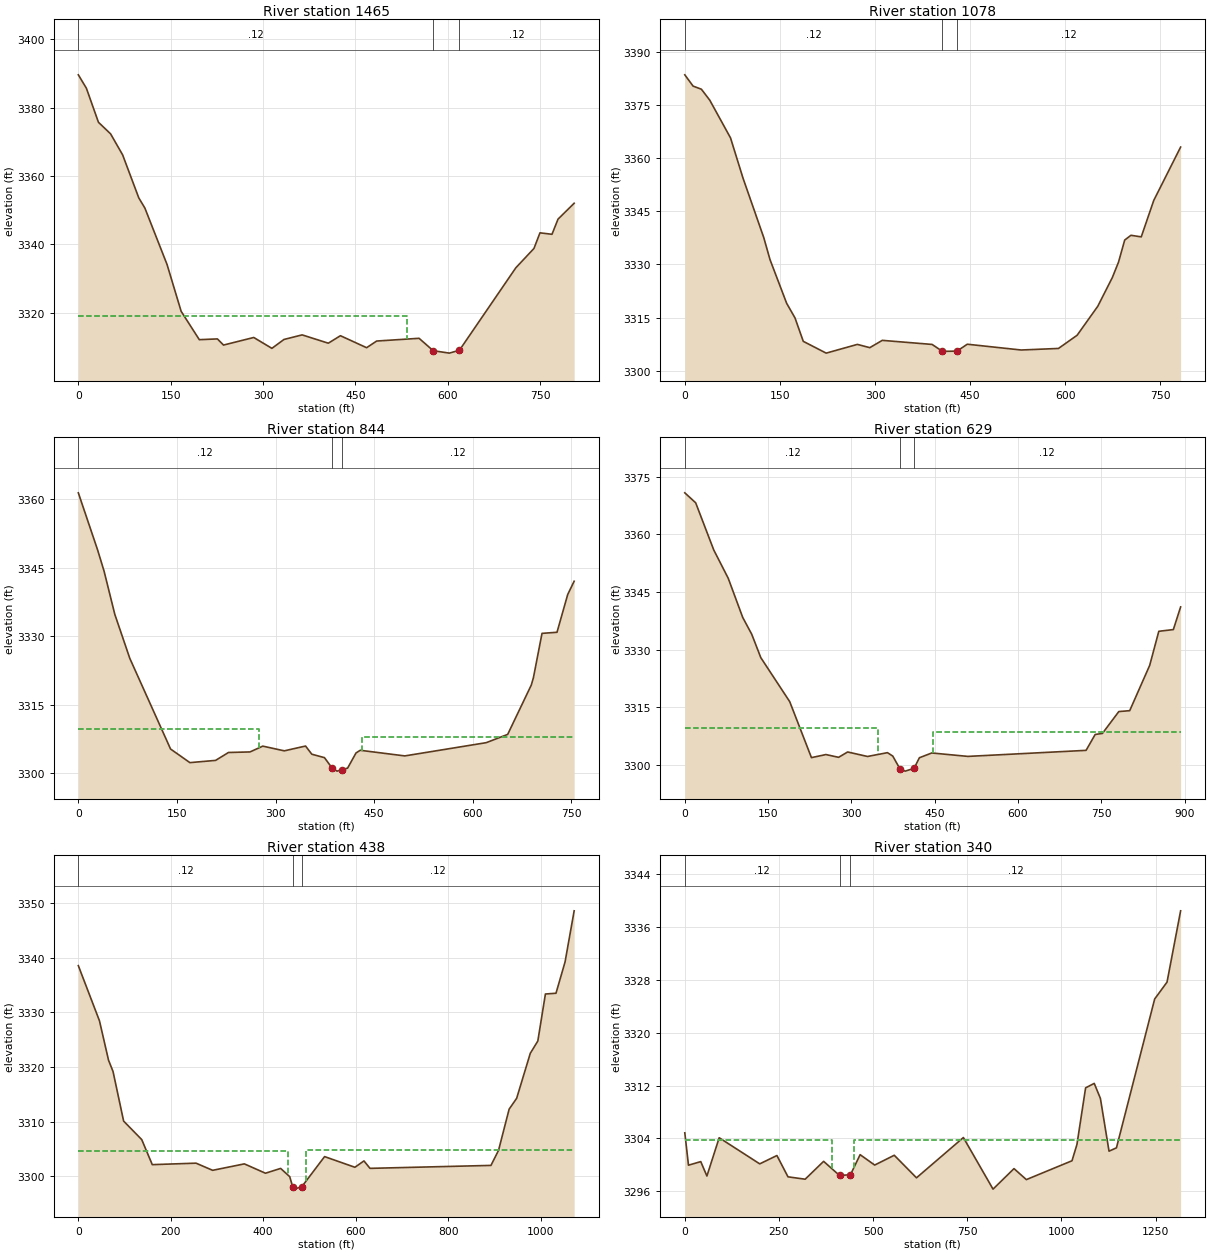
Type RM Length L Ch R = 1 ,1465    ,386.2,386.6,387
XS GIS Cut Line= 4
     2150144.093      433599.998      2150645.02      433470.612
      2150773.22      433430.253     2150926.347      433419.569
#Sta/Elev= 30
       0 3389.64    13.1 3385.71    32.7 3375.74    52.4 3372.36      72 3366.19
    98.2 3353.61   108.1 3350.63   144.1 3334.11     167  3320.4   196.5  3312.1
   225.9 3312.32   235.8 3310.52   284.9 3312.74   314.4 3309.56     334 3312.16
   363.5  3313.5     406 3311.07   425.7 3313.26   468.2 3309.75   484.6  3311.7
   553.4  3312.5   576.4 3308.87   602.6 3308.16     619 3309.01   710.6 3333.15
     740  3338.8   749.8 3343.38   769.3 3342.95   779.1 3347.39   805.3 3352.04
#Mann= 3 , 0 , 0
       0     .12       0   576.4     .04       0     619     .12       0
#XS Ineff= 2 , 0
          533.78 3319.06
Permanent Ineff=
       F       F
Bank Sta=576.4,619
XS Rating Curve= 0 ,0
Exp/Cntr=0.3,0.1

Type RM Length L Ch R = 1 ,1078    ,226.5,233.8,241
XS GIS Cut Line= 3
     2150311.464      433909.813     2150654.517      433836.217
     2151068.791      433716.327
#Sta/Elev= 30
       0 3383.45    13.1 3380.27    26.2 3379.39    39.4  3376.3    72.1 3365.69
    91.8 3354.35   124.6 3337.56   134.4 3331.37   160.7 3319.04   173.8 3314.95
   186.9 3308.33     223 3305.01   272.2 3307.47   291.8 3306.55   311.5 3308.61
   390.1 3307.46   406.4 3305.51   429.3 3305.57   445.6 3307.52   530.6 3305.89
   589.4 3306.33   618.8 3310.04   651.4 3318.21   674.3 3326.28   684.1 3330.64
   693.9 3336.88   703.7 3338.22     720 3337.78   739.7 3348.04   782.1 3363.09
#Mann= 3 , 0 , 0
       0     .12       0   406.4     .04       0   429.3     .12       0
#XS Ineff= 2 , 0
          316.97 3308.34
Permanent Ineff=
       F       F
Bank Sta=406.4,429.3
XS Rating Curve= 0 ,0
Exp/Cntr=0.3,0.1

Type RM Length L Ch R = 1 ,844     ,198.9,215.4,195.8
XS GIS Cut Line= 4
     2150408.801      434062.941     2150739.983      434029.704
     2150864.621      434033.265     2151143.574      433932.367
#Sta/Elev= 30
       0 3361.42    29.4 3348.89    39.2 3344.26    55.5 3334.82    78.3 3325.19
   140.3 3305.35   169.7 3302.37   208.8 3302.86   228.4 3304.59   261.1 3304.71
   280.6 3305.98   313.3 3304.95   345.6    3306   355.2 3304.21   374.4 3303.46
   386.4  3301.1   393.6 3300.51   401.4 3300.84   409.6 3301.17   422.4 3304.49
   428.8 3305.07   496.6 3303.84   620.5 3306.74   653.1 3308.55     689 3319.35
   692.2 3320.94   705.3 3330.66   728.1  3330.9   744.4 3339.17   754.2 3342.07
#Mann= 3 , 0 , 0
       0     .12       0   386.4     .04       0   401.4     .12       0
#XS Ineff= 2 , 0
          275.53 3309.66  431.45            3308
Permanent Ineff=
       F       F
Bank Sta=386.4,401.4
XS Rating Curve= 0 ,0
Exp/Cntr=0.3,0.1

Type RM Length L Ch R = 1 ,629     ,195.7,190.5,185
XS GIS Cut Line= 4
     2150357.759      434222.003     2150725.739      434208.945
     2150818.327      434208.945     2151231.414      434081.933
#Sta/Elev= 30
       0 3370.77    19.6 3368.18    52.1 3355.93    78.2 3348.56   104.3 3338.38
   120.6 3333.98   136.9 3327.91     189 3316.46   228.1 3301.91   254.2 3302.71
     277 3301.99   293.3 3303.38   329.1 3302.21     365  3303.2   374.6 3302.31
   387.8  3298.9     397  3298.4   412.9 3299.12   422.5 3301.88   444.8 3303.12
   509.9 3302.23   722.7  3303.8   739.1 3307.93   752.2 3308.21   781.7 3313.89
   801.3 3314.12   837.3 3325.91   853.7 3334.76   879.9 3335.21     893  3341.1
#Mann= 3 , 0 , 0
       0     .12       0   387.8     .04       0   412.9     .12       0
#XS Ineff= 2 , 0
          348.84  3309.6   447.4         3308.62
Permanent Ineff=
       F       F
Bank Sta=387.8,412.9
XS Rating Curve= 0 ,0
Exp/Cntr=0.5,0.3

Type RM Length L Ch R = 1 ,438     ,101.3,99.6,97.8
XS GIS Cut Line= 4
     2150334.018      434496.207     2150731.674      434390.561
     2150921.599      434353.763     2151345.369      434155.529
#Sta/Elev= 30
       0 3338.54    45.7 3328.46    65.3 3321.26    75.1 3319.17      98  3310.1
   137.2 3306.71     160 3302.13   254.7  3302.4   290.6 3301.09   359.2 3302.27
   404.9 3300.56   437.7 3301.44   457.4 3299.93   463.9 3298.05   467.2 3297.65
   483.6  3298.1   532.8  3303.6   598.4 3301.65     618 3302.81   631.1 3301.45
   892.8 3301.99   909.2 3304.75   932.1 3312.28   948.4 3314.27   977.9  3322.5
   994.2 3324.75  1010.6 3333.35  1033.5 3333.49  1053.1 3339.21  1072.8 3348.57
#Mann= 3 , 0 , 0
       0     .12       0   463.9     .04       0   483.6     .12       0
#XS Ineff= 2 , 0
          454.49  3304.7  493.02         3304.81
Permanent Ineff=
       F       F
Bank Sta=463.9,483.6
XS Rating Curve= 0 ,0
Exp/Cntr=0.5,0.3

Type RM Length L Ch R = 1 ,340     ,144,140.1,136.3
XS GIS Cut Line= 4
     2150411.175      434611.349     2150787.464      434481.963
     2150908.541      434448.726     2151695.544      434546.063
#Sta/Elev= 30
       0 3304.85     9.8 3299.96    42.4  3300.5    58.7 3298.32    91.3 3304.11
     199 3300.16   244.6 3301.42     274  3298.2   319.6 3297.84   368.6 3300.54
   410.8 3298.41   439.8 3298.51   465.5 3301.55   504.2 3299.98   556.2 3301.46
   615.2 3298.05   739.7 3304.14   818.4 3296.34   874.1 3299.44   906.9 3297.78
  1028.1 3300.63  1041.2 3303.09  1064.2 3311.65  1087.1 3312.33  1103.5 3310.06
  1126.4 3302.08  1146.1 3302.58  1247.6 3325.09  1280.4 3327.64  1316.5 3338.42
#Mann= 3 , 0 , 0
       0     .12       0   410.8     .04       0   439.8     .12       0
#XS Ineff= 2 , 0
           390.7 3303.79  448.06          3303.7
Permanent Ineff=
       F       F
Bank Sta=410.8,439.8
XS Rating Curve= 0 ,0
Exp/Cntr=0.5,0.3

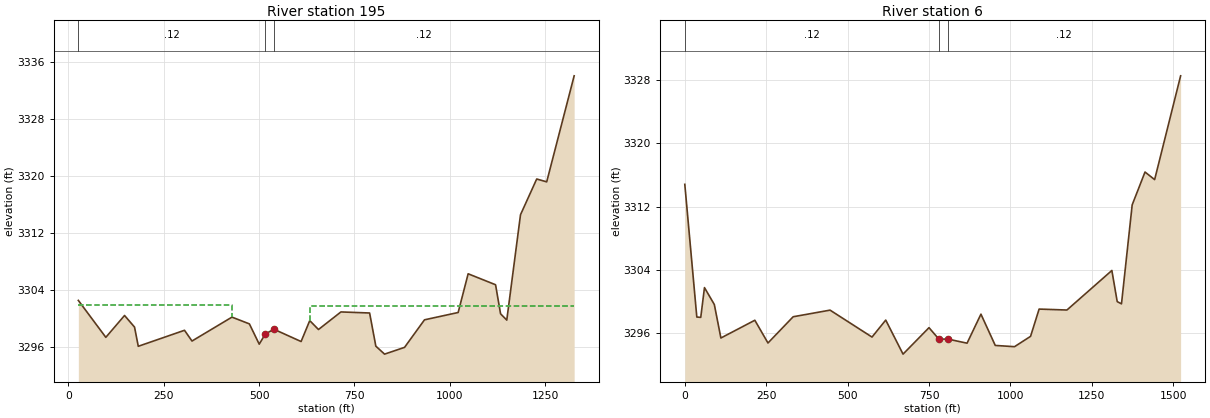
Type RM Length L Ch R = 1 ,195     ,189,189,189
XS GIS Cut Line= 4
2150422.92241463434666.214544678     2150855.125      434611.349
      2151001.13      434542.501     2151703.853      434567.429
#Sta/Elev= 30
    26.2 3302.51    98.3 3297.32   147.4 3300.39   173.6 3298.76   183.4 3296.06
   304.6 3298.31   324.3  3296.8   429.1 3300.16   474.8 3299.21   500.6 3296.36
   516.8 3297.81   539.4 3298.45   610.4 3296.73   633.1 3299.67     656 3298.42
   714.9 3300.89   790.1 3300.74   806.4 3296.08   829.3 3294.96   881.7 3295.91
     934 3299.78  1022.3 3300.81  1048.5 3306.25  1120.4 3304.71  1133.5 3300.63
  1149.8 3299.74  1185.8 3314.55  1228.3 3319.57  1254.5 3319.17  1326.5 3334.07
#Mann= 3 , 0 , 0
    26.2     .12       0   516.8     .04       0   539.4     .12       0
#XS Ineff= 2 , 0
          429.46  3301.8  632.56         3301.71
Permanent Ineff=
       F       F
Bank Sta=516.8,539.4
XS Rating Curve= 0 ,0
Exp/Cntr=0.3,0.1

Type RM Length L Ch R = 1 ,6       ,11,11,11
XS GIS Cut Line= 6
2150326.74750591434704.3144861012150709.98618494434790.414135946
2150921.00970702434815.1505177072151055.96103003434633.900106266
2151111.54789844434562.808954853 2151712.1426887434593.872666137
#Sta/Elev= 30
       03314.833  36.9013298.062  49.0073298.019  60.4393301.782  90.7033299.643
 110.8793295.412  215.123297.656 255.4713294.781 332.8113298.097 446.1813298.934
  575.013295.531 617.1573297.677 670.3313293.375 750.0443296.718 780.1923295.281
 808.659 3295.27 866.9683294.758 909.5783298.427 953.5633294.4731012.7033294.315
1061.9863295.621 1088.273299.0671173.6943298.9481311.6863303.9441328.1143300.012
1341.2563299.7281374.1063312.2391413.5193316.3861443.0793315.4291522.8763328.543
#Mann= 3 , 0 , 0
       0     .12       0 780.192     .04       0 808.659     .12       0
Bank Sta=780.192,808.659
XS Rating Curve= 0 ,0
Exp/Cntr(USF)=0,0
Exp/Cntr=0.3,0.1
LCMann Table=0

Chan Stop Cuts=-1
Use User Specified Reach Order=0
Composite Channel Slope=5